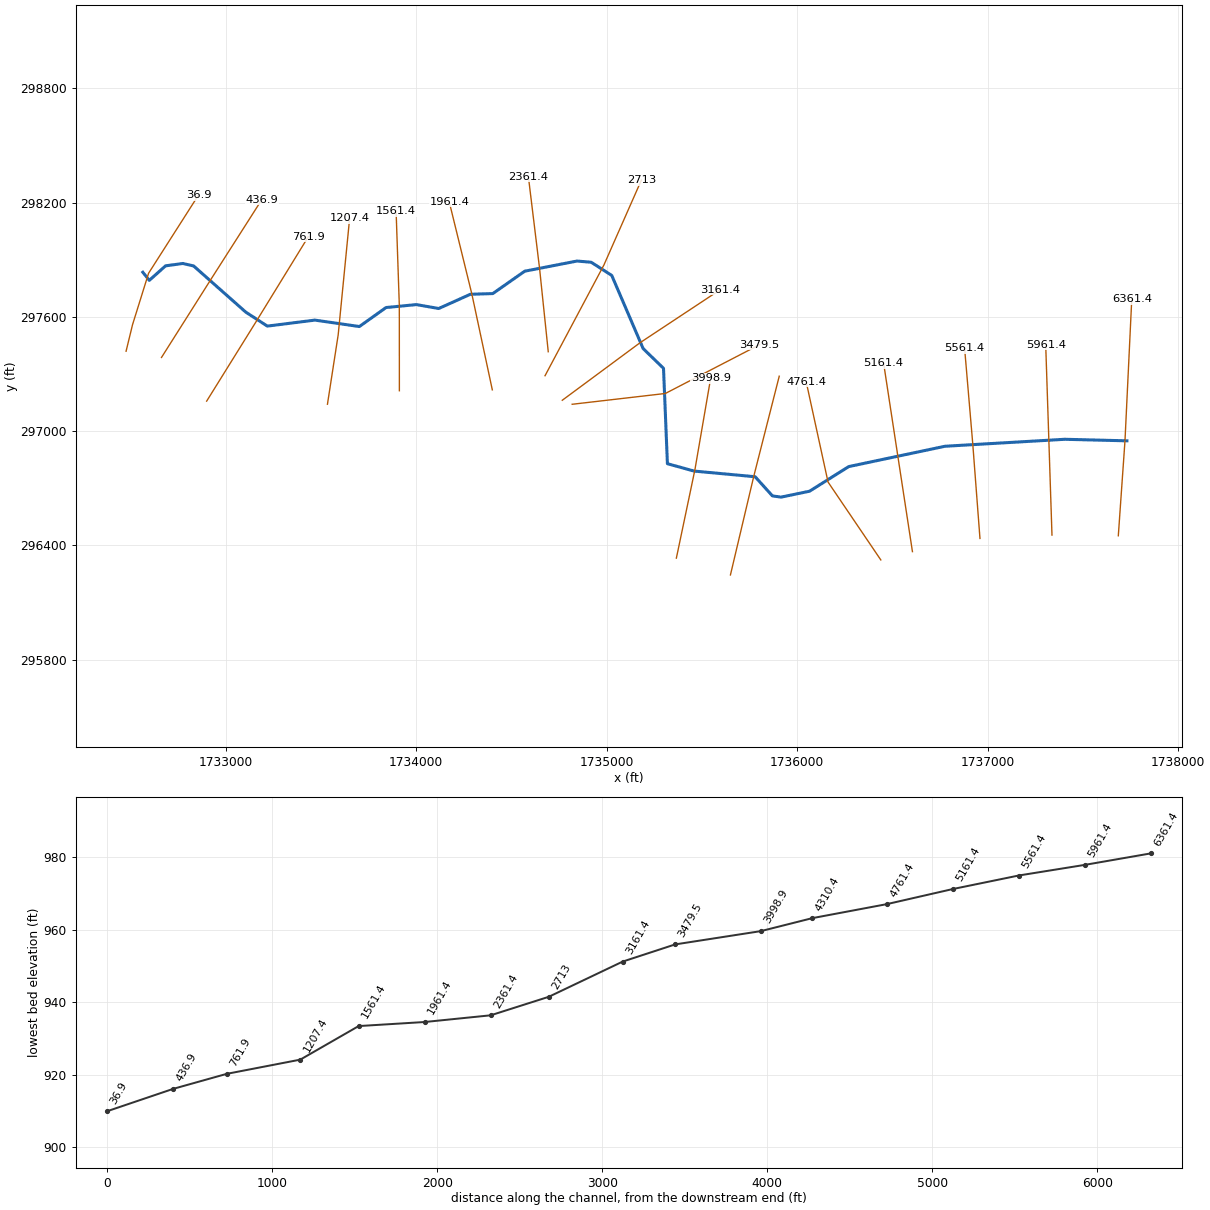
--- JackRn.prj (project) ---

Proj Title=JackRn
Current Plan=p01
Default Exp/Contr=0,0
English Units
Geom File=g01
Flow File=f01
Plan File=p01
BEGIN DESCRIPTION:
END DESCRIPTION:
DSS Export Rating Curves= 0
DSS Export Rating Curve Sorted= 0
DSS Export Volume Flow Curves= 0
DXF OffsetX= 0
DXF OffsetY= 0
DXF ScaleX= 0
DXF ScaleY= 0

--- JackRn.p01 (plan) ---

Plan Title=Floodplain
Program Version=4.00
Geom File=g01
Flow File=f01
K Sum by GR=0
Std Step Tol=0.01
Critical Tol=0.01
Num of Std Step Trials=20
Max Error Tol=0.3
Flow Tol Ratio=0.001
Split Flow NTrial=30
Split Flow Tol=0.02
Split Flow Ratio=0.02
Log Output Level=0
Friction Slope Method=1
Unsteady Friction Slope Method=2
Unsteady Bridges Friction Slope Method=1
Global Log Level=0
CheckData=False
Run HTab=0
Run UNet=0
Run PostProcess=0
UNET Theta=0
UNET Theta Warmup=0
UNET ZTol=0
UNET ZSATol=0
UNET MxIter=0
UNET MaxInSteps=0
UNET DtIC=0
UNET DtMin=0
UNET MaxCRTS=0
UNET WFStab=0
UNET SFStab=0
UNET WFX=0
UNET SFX=0
UNET DSS MLevel=0
UNET DZMax Abort=0
UNET Convert EG Bridges=0
UNET Use Existing IB Tables=0
UNET Froude Limit=0
UNET Froude Power=0
Write IC File=0
Echo Input=False
Echo Output=False
Write Detailed=0

--- JackRn.f01 (steady flow) ---

Flow Title=NFF Regression Equation
Program Version=4.00
Number of Profiles= 1
Profile Names=P100yr
River Rch & RM=JackRn,Main            ,6361.4
832.1404
River Rch & RM=JackRn,Main            ,4310.4
889.1939
River Rch & RM=JackRn,Main            ,2713
979.1084
River Rch & RM=JackRn,Main            ,436.9
1050.478
River Rch & RM=JackRn,Main            ,36.9
1057.102
Boundary for River Rch & Prof#=JackRn,Main            , 1
Up Type= 0
Dn Type= 3
Dn Slope=0.0122
DSS Import GetInterval= 0
DSS Import GetPeak= 0
DSS Import FillOption= 0

--- JackRn.g01 (geometry) ---

Geom Title=USGS 3m DEM
Program Version=4.00

River Reach=JackRn     ,Main
Reach XY= 30
     1737730.523      296948.641     1737404.374      296956.750
     1736775.764      296920.129     1736270.586      296813.395
     1736064.592      296684.025     1735915.247      296653.038
     1735869.802      296659.495     1735779.244      296760.071
     1735458.607      296789.814     1735318.688      296828.554
     1735298.190      297329.493     1735191.467      297432.755
     1735026.529      297817.009     1734918.543      297886.391
     1734843.910      297892.639     1734569.681      297839.330
     1734402.208      297721.882     1734284.488      297718.155
     1734118.258      297643.446     1734001.022      297663.971
     1733841.904      297648.581     1733701.808      297548.743
     1733468.556      297582.530     1733218.678      297551.030
     1733105.853      297624.113     1732831.663      297866.865
     1732775.241      297879.821     1732684.539      297867.524
     1732599.077      297791.271     1732564.967      297833.954

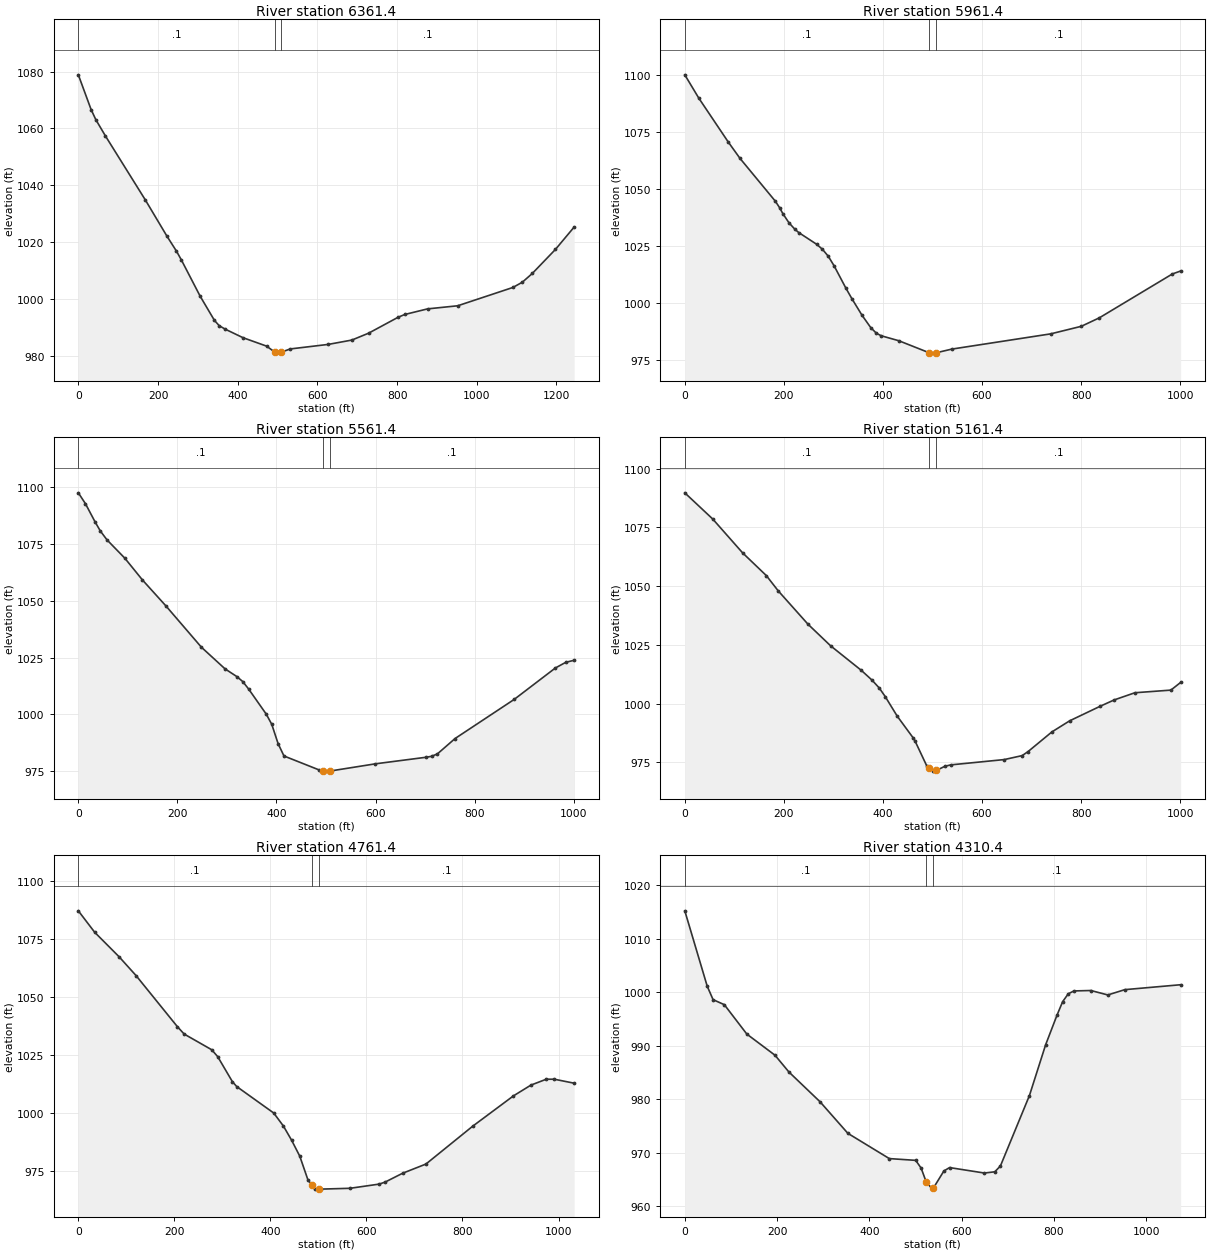
Type RM Length L Ch R = 1 ,6361.4,397.682,400,401.816
XS GIS Cut Line= 3
     1737685.508      296450.069     1737720.548      296949.341
     1737756.079      297692.461
#Sta/Elev= 30
       0 1078.85    32.1 1066.63    44.0 1063.07    67.8 1057.42   168.1 1034.90
   222.5 1022.13   246.3 1016.89   258.2 1013.91   305.9 1001.02   341.6  992.56
   353.5  990.71   368.2  989.50   413.2  986.48   472.5  983.51     493  981.42
   496.3  981.05     508  981.32   531.9  982.52   627.0  984.11   686.5  985.64
   728.6  988.06   802.4  993.64   819.3  994.63   876.6  996.60   952.2  997.69
  1090.6 1004.12  1114.4 1005.97  1139.4 1009.04  1197.6 1017.51  1244.5 1025.36
#Mann= 3 , 0 , 0
       0     0.1       0     493   0.045       0     508     0.1       0
Bank Sta=     493,     508
Exp/Cntr=0.3,0.1

Type RM Length L Ch R = 1 ,5961.4,399.031,400,401.176
XS GIS Cut Line= 3
     1737337.322      296453.768     1737320.836      296953.996
     1737304.350      297454.225
#Sta/Elev= 30
       0 1100.01    28.3 1089.77    87.9 1070.47   111.5 1063.33   182.8 1044.55
   191.4 1041.70   198.1 1039.04   210.4 1035.05   222.7 1032.14   230.3 1030.75
   265.9 1025.69   277.8 1023.47   289.7 1020.38   301.6 1016.13   325.3 1006.36
   337.2 1001.82   357.8  994.49   375.4  989.08   386.9  986.59   396.6  985.49
   432.2  983.31     493  978.08   503.5  977.88     508  978.06   539.1  979.65
   738.6  986.33   800.5  989.65   836.9  993.37   984.3 1012.62  1001.0 1013.92
#Mann= 3 , 0 , 0
       0     0.1       0     493   0.045       0     508     0.1       0
Bank Sta=     493,     508
Exp/Cntr=0.3,0.1

Type RM Length L Ch R = 1 ,5561.4,398.291,400,401.503
XS GIS Cut Line= 3
     1736959.299      296436.119     1736921.278      296935.344
     1736878.698      297433.941
#Sta/Elev= 30
       0 1097.54    14.3 1092.78    34.2 1084.58    44.5 1080.71    58.0 1076.79
    93.7 1068.79   129.5 1059.15   177.1 1047.66   248.5 1029.53   296.2 1020.00
   320.0 1016.60   331.9 1014.42   343.8 1011.13   379.4 1000.06   390.5  995.59
   403.3  987.08   415.2  981.62   486.7  975.43   493.2  975.17   498.6  974.95
   508.2  974.99   599.9  978.17   701.1  981.03   713.1  981.47   725.0  982.54
   760.7  989.32   879.9 1006.52   963.3 1020.40   984.2 1022.88  1001.1 1023.79
#Mann= 3 , 0 , 0
       0     0.1       0   493.2   0.045       0   508.2     0.1       0
Bank Sta=   493.2,   508.2
Exp/Cntr=0.3,0.1

Type RM Length L Ch R = 1 ,5161.4,389.909,400,400.97
XS GIS Cut Line= 3
     1736604.881      296366.881     1736529.229      296861.631
     1736453.577      297356.380
#Sta/Elev= 30
       0 1089.69    56.5 1078.52   116.6 1064.16   164.6 1054.46   188.6 1047.96
   248.7 1033.76   294.5 1024.54   356.4 1014.11   377.9 1009.97   392.8 1006.55
   404.8 1002.89   428.8  994.63   461.2  985.32   464.9  984.00   488.9  973.26
     493  972.57   500.5  971.21     508  971.52   524.9  973.26   536.9  973.87
   645.0  976.13   681.1  977.82   693.1  979.55   741.1  987.90   777.1  992.64
   838.5  998.82   866.8 1001.52   908.7 1004.58   981.3 1005.70  1001.0 1008.97
#Mann= 3 , 0 , 0
       0     0.1       0     493   0.045       0     508     0.1       0
Bank Sta=     493,     508
Exp/Cntr=0.3,0.1

Type RM Length L Ch R = 1 ,4761.4,469.952,450.967,440.759
XS GIS Cut Line= 3
     1736438.782      296323.341     1736161.807      296732.225
     1736047.049      297258.969
#Sta/Elev= 30
       0 1087.13    34.0 1077.89    85.1 1067.26   120.1 1059.22   206.1 1037.19
   220.4 1033.96   277.8 1027.18   290.2 1024.22   320.8 1013.43   329.8 1011.31
   406.9  999.89   427.0  994.29   444.1  988.17   461.2  981.25   478.3  970.95
   486.4  968.85   492.9  967.16   501.4  967.07   504.4  967.04   565.9  967.40
   626.6  969.21   638.8  970.07   675.2  973.88   723.9  977.86   821.1  994.16
   906.1 1007.27   942.6 1011.93   974.5 1014.46   991.2 1014.47  1032.6 1012.75
#Mann= 3 , 0 , 0
       0     0.1       0   486.4   0.045       0   501.4     0.1       0
Bank Sta=   486.4,   501.4
Exp/Cntr=0.3,0.1

Type RM Length L Ch R = 1 ,4310.4,311.009,311.578,313.042
XS GIS Cut Line= 3
     1735649.489      296244.351     1735772.238      296763.411
     1735905.702      297288.008
#Sta/Elev= 30
       0 1015.22    48.6 1001.12    61.3  998.61    85.7  997.67   134.5  992.17
   195.5  988.22   225.7  985.08   293.1  979.52   353.5  973.61   443.3  968.89
   500.5  968.56   512.3  967.10   523.6  964.44   537.1  963.18   538.6  963.35
   561.6  966.58   573.9  967.21   649.3  966.19   671.9  966.42   684.1  967.51
   747.0  980.68   782.1  990.17   806.6  995.67   818.9  998.22   831.1  999.70
   843.4 1000.24   880.1 1000.32   916.9  999.49   953.7 1000.48  1074.7 1001.40
#Mann= 3 , 0 , 0
       0     0.1       0   523.6   0.045       0   538.6     0.1       0
Bank Sta=   523.6,   538.6
Exp/Cntr=0.3,0.1

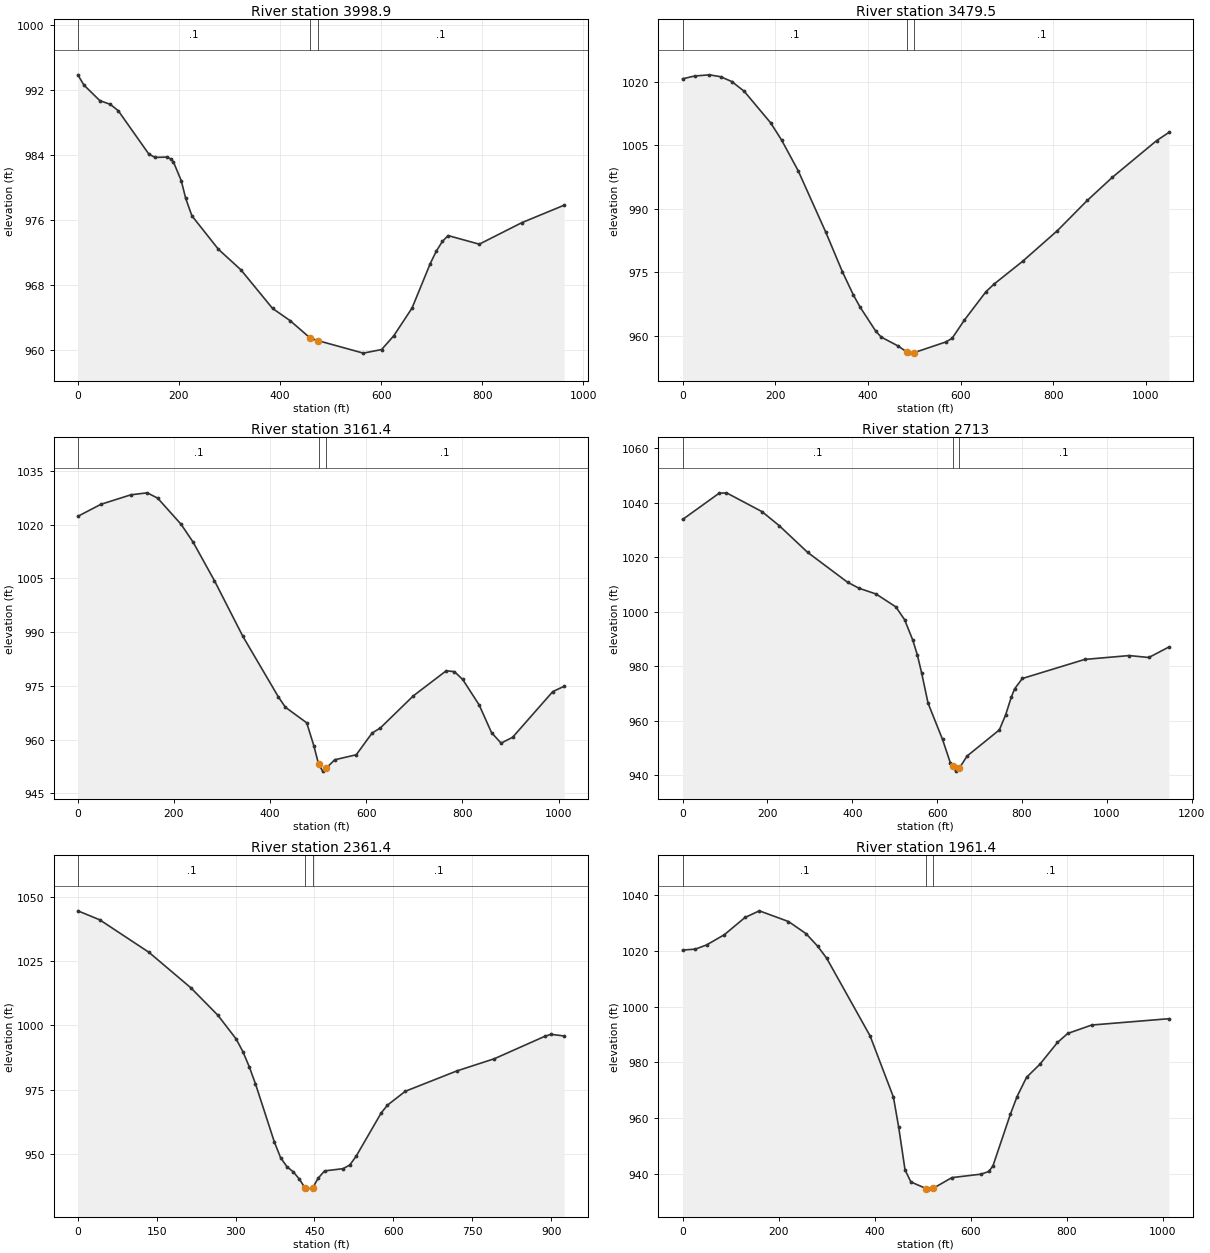
Type RM Length L Ch R = 1 ,3998.9,548.177,519.332,498.727
XS GIS Cut Line= 3
     1735365.667      296332.661     1735463.041      296796.907
     1735545.663      297277.154
#Sta/Elev= 30
       0  993.88    12.0  992.62    43.5  990.70    64.1  990.25    79.9  989.46
   140.6  984.10   152.7  983.71   177.0  983.75   184.5  983.48   189.1  983.14
   204.5  980.84   213.3  978.66   225.5  976.52   278.0  972.39   322.5  969.86
   385.0  965.11   419.6  963.61   459.3  961.47   474.3  961.15   564.5  959.60
   600.7  960.04   624.8  961.74   660.9  965.15   697.0  970.64   709.1  972.19
   721.1  973.37   732.2  974.08   793.9  973.02   877.7  975.66   961.7  977.82
#Mann= 3 , 0 , 0
       0     0.1       0   459.3   0.045       0   474.3     0.1       0
Bank Sta=   459.3,   474.3
Exp/Cntr=0.3,0.1

Type RM Length L Ch R = 1 ,3479.5,305.69,318.123,320.556
XS GIS Cut Line= 3
     1734818.791      297140.570     1735307.824      297197.269
     1735802.902      297453.732
#Sta/Elev= 30
       0 1020.66    25.8 1021.32    57.9 1021.60    82.1 1021.15   106.0 1020.02
   132.9 1017.72   189.7 1010.31   213.6 1006.22   249.4  998.97   309.2  984.42
   345.0  975.10   368.5  969.67   383.0  966.80   416.8  961.13   428.7  959.71
   464.6  957.65   483.9  956.21   488.5  955.93   498.9  956.02   568.2  958.57
   581.6  959.42   608.4  963.76   654.8  970.43   672.4  972.24   734.0  977.61
   808.9  984.83   873.4  991.96   927.8  997.44  1022.9 1006.06  1049.6 1008.01
#Mann= 3 , 0 , 0
       0     0.1       0   483.9   0.045       0   498.9     0.1       0
Bank Sta=   483.9,   498.9
Exp/Cntr=0.3,0.1

Type RM Length L Ch R = 1 ,3161.4,438.343,448.418,460.296
XS GIS Cut Line= 3
     1734766.845      297161.646     1735175.581      297464.111
     1735595.253      297741.738
#Sta/Elev= 30
       0 1022.37    47.9 1025.72   110.4 1028.38   144.4 1028.93   166.1 1027.44
   214.8 1020.14   239.9 1015.13   284.2 1004.38   343.3  988.84   417.2  971.92
   431.9  969.03   476.2  964.68   491.0  958.27     501  953.06   509.4  951.19
     516  951.93   534.4  954.36   579.2  955.76   612.2  961.83   629.3  963.25
   697.9  972.21   766.4  979.22   783.5  978.98   800.7  976.79   835.0  969.66
   860.7  961.94   880.5  959.01   904.5  960.64   988.1  973.41  1011.7  974.89
#Mann= 3 , 0 , 0
       0     0.1       0     501   0.045       0     516     0.1       0
Bank Sta=     501,     516
Exp/Cntr=0.3,0.1

Type RM Length L Ch R = 1 ,2713,349.136,351.583,383.723
XS GIS Cut Line= 3
     1734676.320      297290.492     1734985.560      297872.282
     1735182.269      298318.153
#Sta/Elev= 30
       0 1033.83    85.9 1043.45   103.4 1043.61   187.0 1036.72   227.4 1031.60
   294.6 1021.77   388.7 1010.80   415.6 1008.60   456.0 1006.47   502.6 1001.75
   523.2  997.04   542.4  989.60   553.2  984.15   563.5  977.41   578.5  966.41
   612.6  953.10   630.8  944.61   636.8  943.27   644.2  941.46   651.8  942.47
   670.7  947.03   746.5  956.58   761.5  962.17   774.5  968.52   782.5  971.66
   800.7  975.46   947.8  982.46  1052.6  983.88  1098.9  983.17  1146.2  987.02
#Mann= 3 , 0 , 0
       0     0.1       0   636.8   0.045       0   651.8     0.1       0
Bank Sta=   636.8,   651.8
Exp/Cntr=0.3,0.1

Type RM Length L Ch R = 1 ,2361.4,397.228,400,403.058
XS GIS Cut Line= 3
     1734693.191      297416.500     1734647.691      297853.228
     1734588.973      298335.249
#Sta/Elev= 30
       0 1044.47    41.6 1040.98   134.9 1028.40   214.6 1014.62   266.2 1003.93
   301.1  994.66   313.9  989.74   325.9  983.92   337.8  977.24   373.6  954.73
   385.5  948.60   397.5  945.09   409.7  943.07   421.3  940.24   431.6  936.92
   433.3  936.36   446.6  936.91   457.2  940.67   469.2  943.44   504.4  944.31
   517.0  945.73   529.0  949.08   576.8  965.94   588.8  969.00   622.8  974.38
   720.3  982.25   792.1  987.02   887.8  995.71   899.7  996.50   924.7  995.85
#Mann= 3 , 0 , 0
       0     0.1       0   431.6   0.045       0   446.6     0.1       0
Bank Sta=   431.6,   446.6
Exp/Cntr=0.3,0.1

Type RM Length L Ch R = 1 ,1961.4,404.853,400,395.22
XS GIS Cut Line= 3
     1734399.616      297216.234     1734292.036      297720.006
     1734173.403      298203.585
#Sta/Elev= 30
       0 1020.34    26.3 1020.66    49.9 1022.17    87.0 1025.86   130.0 1032.04
   159.8 1034.42   220.5 1030.58   257.0 1026.24   281.2 1021.75   300.0 1017.43
   390.5  989.53   439.1  967.57   450.1  956.76   463.3  941.45   475.5  937.09
   507.6  934.69   511.9  934.51   522.6  934.86   560.8  938.64   621.9  939.89
   637.8  940.84   646.4  942.84   683.0  961.52   696.7  967.73   716.4  974.64
   744.2  979.34   780.8  987.15   802.3  990.40   852.2  993.42  1013.0  995.69
#Mann= 3 , 0 , 0
       0     0.1       0   507.6   0.045       0   522.6     0.1       0
Bank Sta=   507.6,   522.6
Exp/Cntr=0.3,0.1

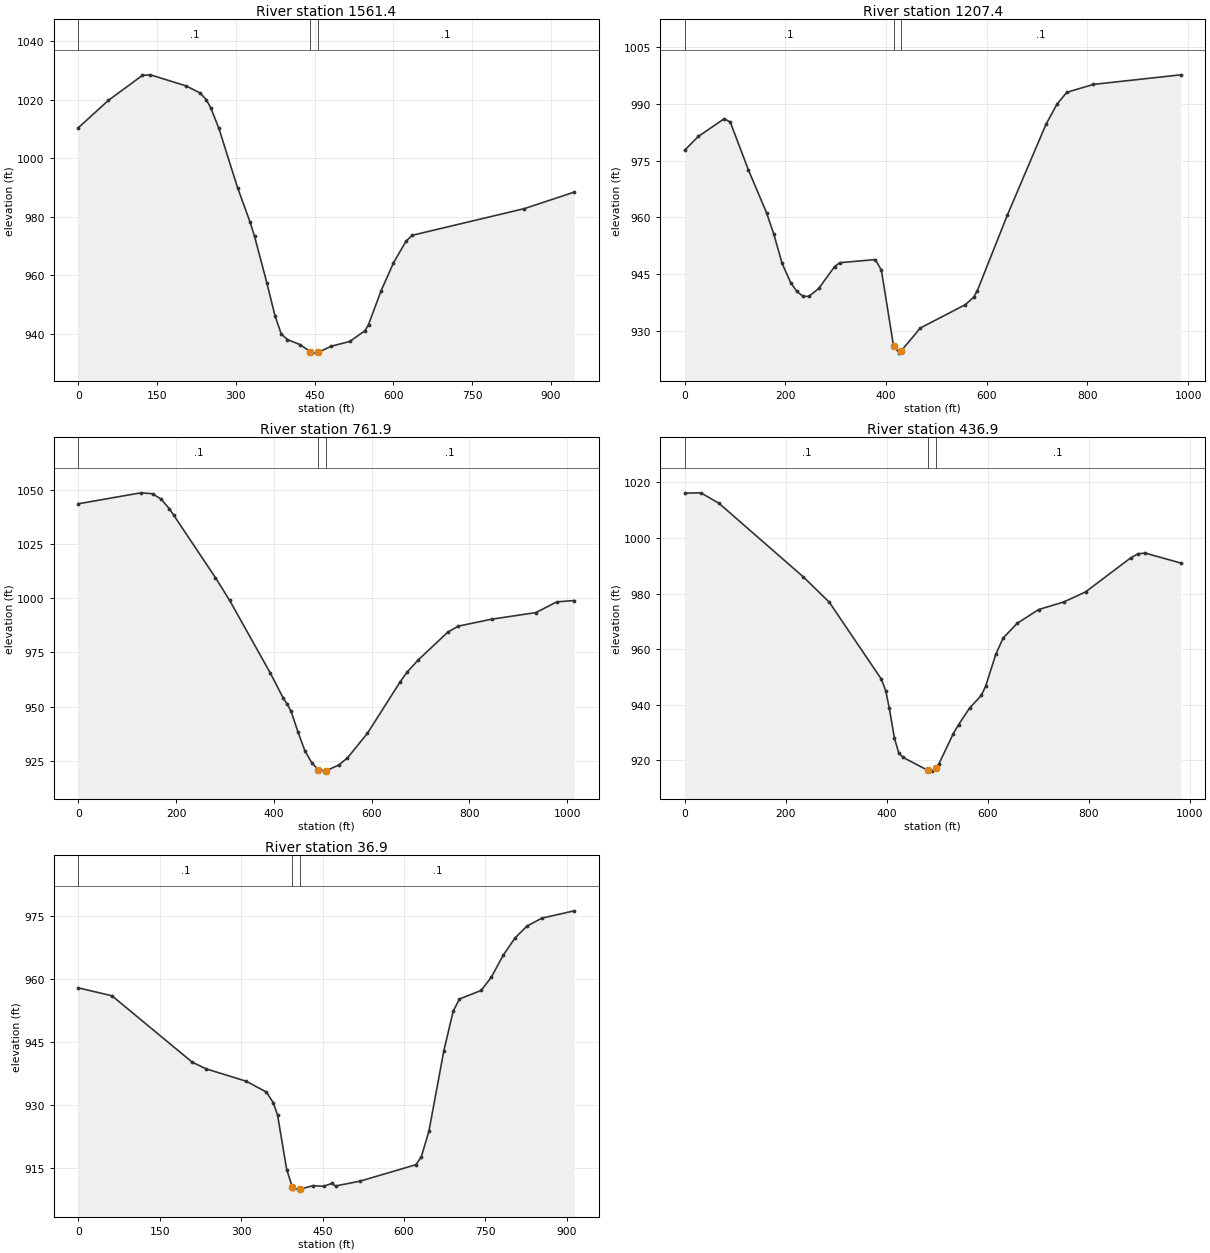
Type RM Length L Ch R = 1 ,1561.4,356.167,354.023,351.127
XS GIS Cut Line= 3
     1733911.758      297211.579     1733911.426      297660.907
     1733894.502      298155.779
#Sta/Elev= 30
       0 1010.38    57.3 1019.73   122.1 1028.27   137.2 1028.45   205.2 1024.68
   232.2 1022.22   244.1 1019.87   252.6 1017.03   267.8 1010.12   303.4  989.89
   327.2  978.12   335.7  973.28   359.4  957.19   374.7  946.11   386.6  939.94
   398.4  938.00   422.2  936.32   441.8  933.91   445.9  933.39   456.8  933.62
   481.6  935.75   517.2  937.38   546.0  941.05   552.8  943.16   576.6  954.63
   600.3  964.21   624.1  971.60   636.0  973.64   849.8  982.76   944.5  988.38
#Mann= 3 , 0 , 0
       0     0.1       0   441.8   0.045       0   456.8     0.1       0
Bank Sta=   441.8,   456.8
Exp/Cntr=0.3,0.1

Type RM Length L Ch R = 1 ,1207.4,455.836,445.443,435.141
XS GIS Cut Line= 3
     1733534.174      297140.769     1733590.598      297505.648
     1733650.784      298118.795
#Sta/Elev= 30
       0  977.78    27.0  981.39    78.4  986.06    90.4  985.16   126.4  972.53
   162.5  961.20   177.0  955.51   193.4  947.82   210.5  942.73   222.5  940.47
   234.5  939.16   246.5  939.09   266.3  941.22   297.5  946.97   307.9  948.02
   378.6  948.84   390.6  946.07   414.8  926.05   426.4  924.12   429.8  924.68
   468.1  930.76   557.6  936.94   573.9  938.88   581.4  940.66   641.1  960.64
   718.0  984.65   739.7  989.92   759.1  993.04   812.0  995.13   985.3  997.66
#Mann= 3 , 0 , 0
       0     0.1       0   414.8   0.045       0   429.8     0.1       0
Bank Sta=   414.8,   429.8
Exp/Cntr=0.3,0.1

Type RM Length L Ch R = 1 ,761.9,325.187,324.996,324.648
XS GIS Cut Line= 3
     1732900.147      297157.073     1733160.038      297575.012
     1733433.609      298020.334
#Sta/Elev= 30
       0 1043.64   127.9 1048.69   151.9 1048.28   169.9 1045.68   186.4 1041.31
   195.0 1038.44   280.4 1009.59   309.7  999.01   392.8  965.50   419.1  954.01
   427.7  951.08   435.5  947.73   449.5  938.24   463.5  929.68   477.4  924.16
   490.8  920.93   505.3  920.20   505.8  920.24   533.2  923.07   550.7  926.31
   591.7  937.70   658.6  961.44   672.6  965.87   695.2  971.46   756.2  984.41
   777.5  987.15   845.6  990.34   936.3  993.40   979.1  998.35  1014.6  998.97
#Mann= 3 , 0 , 0
       0     0.1       0   490.8   0.045       0   505.8     0.1       0
Bank Sta=   490.8,   505.8
Exp/Cntr=0.3,0.1

Type RM Length L Ch R = 1 ,436.9,394.715,400.058,402.827
XS GIS Cut Line= 3
     1732663.105      297386.445     1732927.726      297804.682
     1733189.814      298215.384
#Sta/Elev= 30
       0 1016.15    31.9 1016.27    67.9 1012.48   234.6  986.03   286.3  976.86
   389.5  949.13   398.1  944.97   405.0  938.76   415.3  927.87   423.9  922.56
   432.5  920.98   481.9  916.29   489.3  916.05   496.9  917.04   503.4  918.68
   531.6  929.48   542.3  932.80   564.4  938.85   587.4  943.31   595.9  946.66
   616.1  958.18   630.6  963.99   658.3  969.27   700.6  974.22   750.7  976.98
   793.7  980.57   883.7  992.91   897.8  994.32   911.8  994.57   982.1  991.00
#Mann= 3 , 0 , 0
       0     0.1       0   481.9   0.045       0   496.9     0.1       0
Bank Sta=   481.9,   496.9
Exp/Cntr=0.3,0.1

Type RM Length L Ch R = 1 ,36.9,52.088,36.884,23.066
XS GIS Cut Line= 4
     1732477.154      297419.130     1732511.008      297558.311
     1732595.334      297828.674     1732857.422      298239.376
#Sta/Elev= 30
       0  957.91    62.0  956.01   209.8  940.18   235.5  938.58   309.3  935.63
   346.6  933.04   359.1  930.50   367.0  927.60   383.9  914.55   394.3  910.38
   396.4  909.88   409.3  909.89   432.7  910.72   451.7  910.55   467.1  911.24
   473.8  910.63   519.1  911.79   621.8  915.70   631.8  917.55   645.9  923.70
   673.4  942.90   690.6  952.33   702.2  955.25   742.2  957.29   760.7  960.43
   782.8  965.70   804.8  969.85   826.9  972.68   854.0  974.54   913.5  976.29
#Mann= 3 , 0 , 0
       0     0.1       0   394.3   0.045       0   409.3     0.1       0
Bank Sta=   394.3,   409.3
Exp/Cntr=0.3,0.1